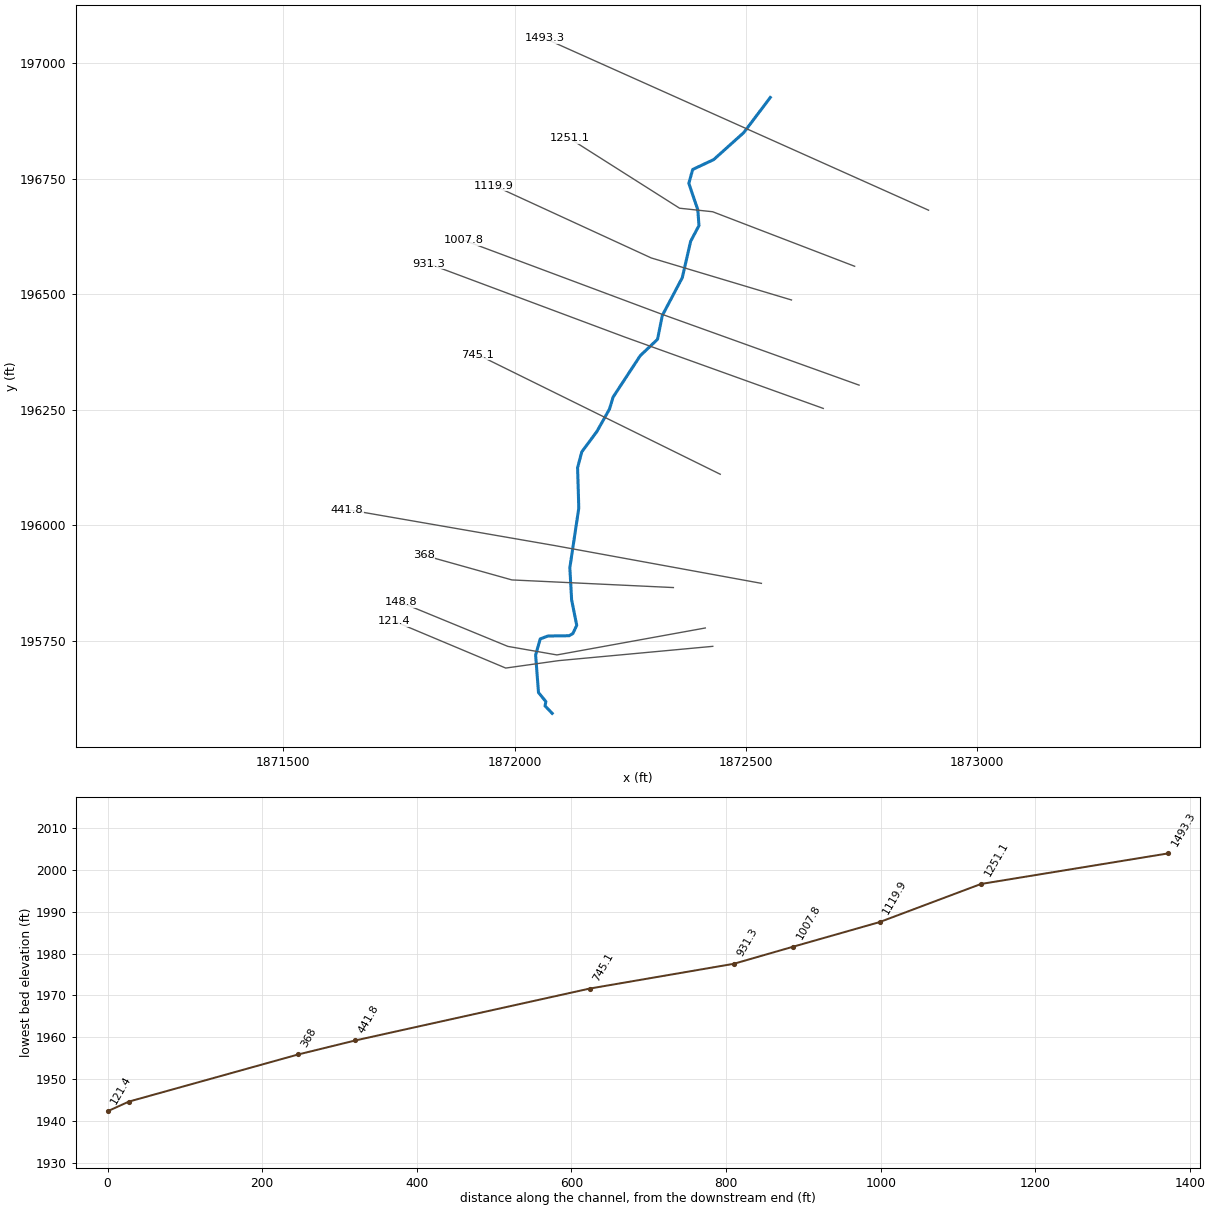
--- ComerBr.prj (project) ---

Proj Title=ComerBr
Current Plan=p01
Default Exp/Contr=0,0
English Units
Geom File=g01
Flow File=f01
Plan File=p01
BEGIN DESCRIPTION:
END DESCRIPTION:
DSS Export Rating Curves= 0
DSS Export Rating Curve Sorted= 0
DSS Export Volume Flow Curves= 0
DXF OffsetX= 0
DXF OffsetY= 0
DXF ScaleX= 0
DXF ScaleY= 0

--- ComerBr.p01 (plan) ---

Plan Title=Floodplain
Program Version=4.00
Geom File=g01
Flow File=f01
K Sum by GR=0
Std Step Tol=0.01
Critical Tol=0.01
Num of Std Step Trials=20
Max Error Tol=0.3
Flow Tol Ratio=0.001
Split Flow NTrial=30
Split Flow Tol=0.02
Split Flow Ratio=0.02
Log Output Level=0
Friction Slope Method=1
Unsteady Friction Slope Method=2
Unsteady Bridges Friction Slope Method=1
Global Log Level=0
CheckData=False
Run HTab=0
Run UNet=0
Run PostProcess=0
UNET Theta=0
UNET Theta Warmup=0
UNET ZTol=0
UNET ZSATol=0
UNET MxIter=0
UNET MaxInSteps=0
UNET DtIC=0
UNET DtMin=0
UNET MaxCRTS=0
UNET WFStab=0
UNET SFStab=0
UNET WFX=0
UNET SFX=0
UNET DSS MLevel=0
UNET DZMax Abort=0
UNET Convert EG Bridges=0
UNET Use Existing IB Tables=0
UNET Froude Limit=0
UNET Froude Power=0
Write IC File=0
Echo Input=False
Echo Output=False
Write Detailed=0

--- ComerBr.f01 (steady flow) ---

Flow Title=NFF Regression Equation
Program Version=4.00
Number of Profiles=1
Profile Names=P100yr
River Rch & RM=ComerBr,Main      ,1493.3
558.0446
River Rch & RM=ComerBr,Main      ,148.8
579.1761
Boundary for River Rch & Prof#=ComerBr,Main      ,1
Up Type=0
Dn Type=3
Dn Slope=0.0649

--- ComerBr.g01 (geometry) ---

Geom Title=USGS 10m DEM
Program Version=4.00

River Reach=ComerBr         ,Main
Reach XY= 30
     1872553.106      196926.171     1872495.857      196850.141
     1872430.771      196791.626     1872385.345      196770.223
      1872376.93      196740.302     1872396.355      196682.981
     1872398.936      196648.793     1872380.874      196614.605
     1872362.812      196535.907     1872319.593      196453.984
     1872309.272      196402.378     1872271.858        196366.9
     1872213.157      196277.236     1872205.416      196251.433
     1872178.324      196203.054     1872145.425      196158.544
     1872136.394      196124.355     1872138.975      196036.627
     1872119.623      195907.614     1872123.493      195837.947
     1872134.517      195782.953     1872126.102       195765.07
     1872117.974      195760.426     1872071.927      195759.811
     1872055.622      195753.499     1872045.629      195718.785
     1872051.843      195637.408     1872067.719      195617.799
     1872065.946      195608.497     1872081.459      195592.279

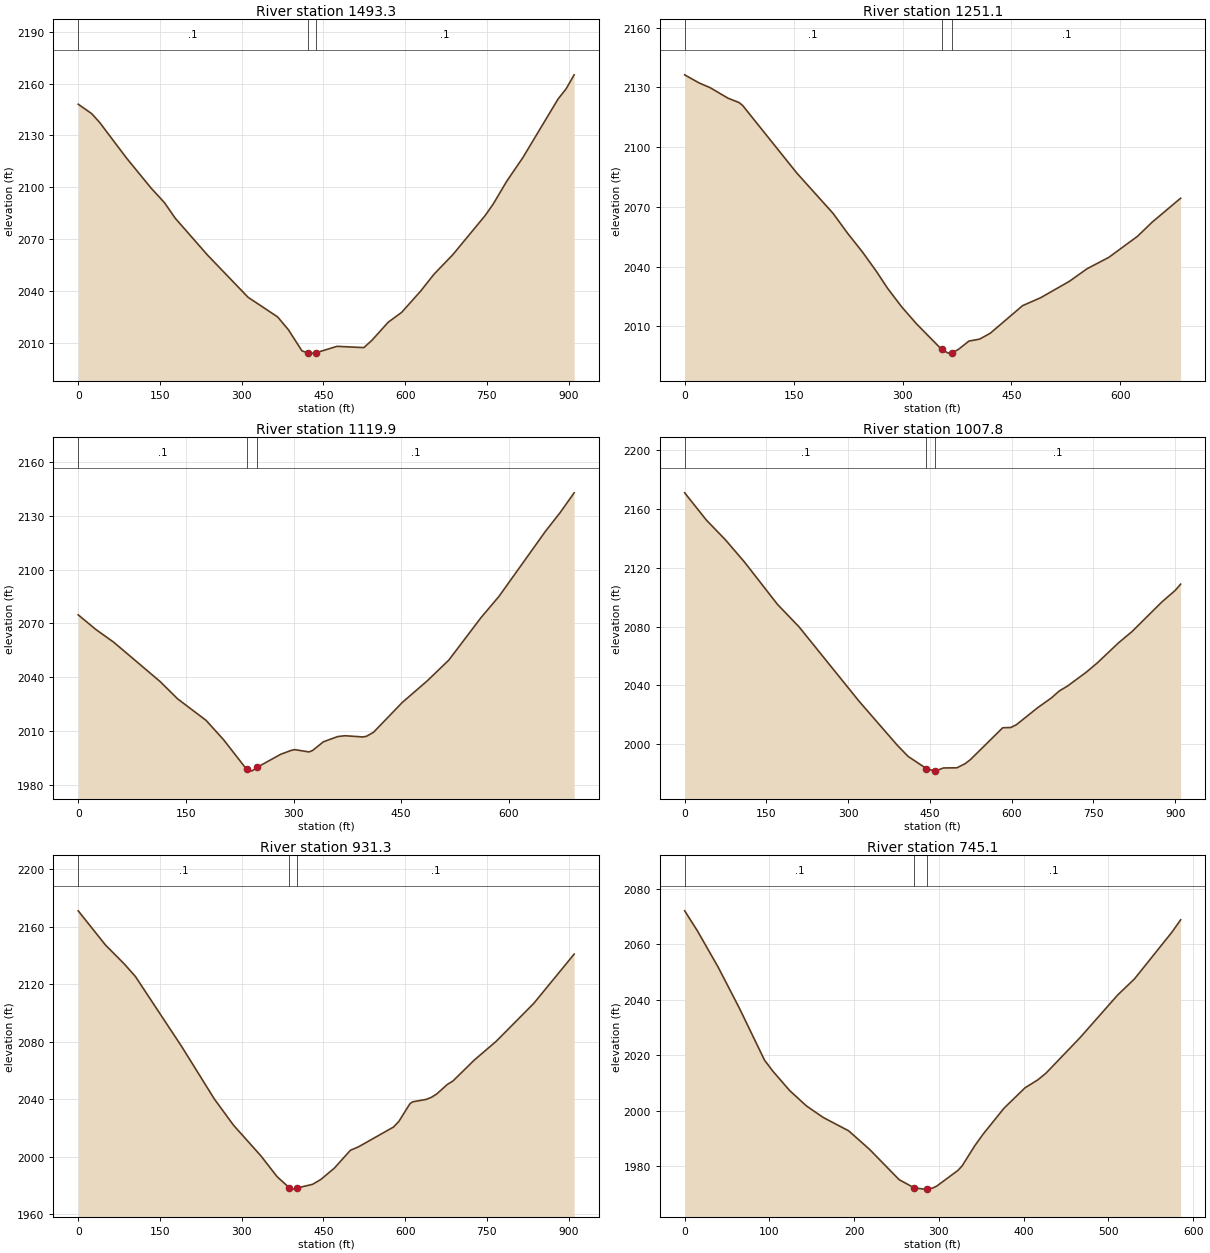
Type RM Length L Ch R = 1 ,1493.3  ,234.8,242.1,248.7
XS GIS Cut Line= 3
     1872895.458      196682.001     1872480.262      196868.114
     1872065.067      197054.226
#Sta/Elev= 30
       0 2148.13    24.7 2142.68    39.6 2137.46      89 2116.78   133.5  2099.6
   158.3 2091.05     178 2082.06   237.4 2060.65   311.6 2036.25     366 2024.82
   385.8 2017.36   410.5  2005.2   421.7 2003.93   430.3 2003.86   436.7 2004.11
   474.8 2007.79   524.2 2007.06   539.1 2011.35   568.8 2021.76   593.5 2027.49
   628.1 2039.73   652.8 2049.58   687.4 2060.93   746.8 2083.65   761.6 2090.34
   786.4 2103.53     816 2117.24   880.3 2151.04   895.2 2157.04     910 2165.16
#Mann= 3 , 0 , 0
       0      .1       0   421.7    .045       0   436.7      .1       0
Bank Sta=421.7,436.7
XS Rating Curve= 0 ,0
Exp/Cntr=0.3,0.1

Type RM Length L Ch R = 1 ,1251.1  ,135.5,131.2,127.7
XS GIS Cut Line= 4
     1872735.609      196560.553     1872428.525      196678.662
     1872356.907      196686.328     1872119.004      196837.484
#Sta/Elev= 30
       0 2136.32    19.9 2132.24    34.9  2129.9    59.8 2124.56    74.8 2122.42
    79.8 2120.95   154.5 2086.96   204.4 2066.73   224.3 2056.78   244.3  2047.6
   264.2 2037.53   279.2 2029.22   299.1 2019.68     319 2011.37   353.7 1998.49
   362.6 1996.64   367.4 1996.57   368.7 1996.74     377 1998.46   391.4 2002.62
     406 2003.59   420.8 2006.56   465.3 2020.41     490 2024.36   529.6  2032.6
   554.3 2038.99     584 2044.65   623.6 2055.26   643.3  2062.2   682.9 2074.36
#Mann= 3 , 0 , 0
       0      .1       0   353.7    .045       0   368.7      .1       0
Bank Sta=353.7,368.7
XS Rating Curve= 0 ,0
Exp/Cntr=0.3,0.1

Type RM Length L Ch R = 1 ,1119.9  ,113.3,112.1,110.6
XS GIS Cut Line= 3
     1872598.954      196487.598     1872295.703      196578.601
     1871955.678      196735.247
#Sta/Elev= 30
       0 2074.74    24.7 2066.53    49.5 2059.44   113.8 2037.61   138.5 2027.84
   178.1 2015.84   202.8  2004.9   234.5 1988.57   237.5 1987.48   242.4 1987.67
   249.5 1989.64     282 1996.86   296.8 1999.06   301.8 1999.48   321.6  1998.2
   326.6 1999.02   341.6 2003.85   361.5 2006.77   371.5 2007.25   396.5 2006.56
   401.5 2006.91   411.4 2009.14   451.4 2025.77   486.3 2037.88   516.3 2049.44
   561.2 2073.18   586.2 2085.01     651 2121.37     671 2131.57     691 2142.86
#Mann= 3 , 0 , 0
       0      .1       0   234.5    .045       0   249.5      .1       0
Bank Sta=234.5,249.5
XS Rating Curve= 0 ,0
Exp/Cntr=0.3,0.1

Type RM Length L Ch R = 1 ,1007.8  ,75.8,76.5,78.5
XS GIS Cut Line= 3
     1872745.187      196303.149      1872317.09      196457.264
      1871890.91      196616.748
#Sta/Elev= 30
       0 2171.15      40 2152.51      75 2139.06     110 2123.89     170  2095.3
     210 2079.81     320  2029.2     390 1999.29     410 1991.61   443.7 1983.32
   458.7 1981.62   459.9  1981.6   474.8 1983.76   499.5 1983.86   514.4 1986.63
   524.2 1989.42   583.6 2011.14   598.4 2011.32   608.3 2013.12   647.9 2024.86
   672.6 2031.37   687.5 2036.22   702.3  2039.5   736.9 2048.98   756.7 2055.15
   796.3 2069.06     821 2076.71   875.4 2096.75   900.1  2104.7     910 2108.94
#Mann= 3 , 0 , 0
       0      .1       0   443.7    .045       0   458.7      .1       0
Bank Sta=443.7,458.7
XS Rating Curve= 0 ,0
Exp/Cntr=0.3,0.1

Type RM Length L Ch R = 1 ,931.3   ,189.7,186.3,181.7
XS GIS Cut Line= 3
     1872667.731      196252.711     1872239.635      196406.826
     1871813.455      196566.311
#Sta/Elev= 30
       0 2170.98      50 2147.24      85 2133.86     105 2125.32     190 2076.58
     250 2040.08     285 2021.96     335 2000.77     365 1986.17     387 1978.64
     395 1977.54     402 1978.36     430 1980.87     445 1984.21   469.8 1992.06
   499.5 2004.56   514.4 2006.96   578.6  2020.7   588.5 2024.67   608.3 2036.72
   613.3 2038.19     638 2039.86   647.9 2041.31   657.8 2043.68   677.6 2050.38
   687.5 2052.67     727 2067.34   766.6 2080.16   835.8  2106.6     910 2140.88
#Mann= 3 , 0 , 0
       0      .1       0     387    .045       0     402      .1       0
Bank Sta=387,402
XS Rating Curve= 0 ,0
Exp/Cntr=0.3,0.1

Type RM Length L Ch R = 1 ,745.1   ,297,303.2,309.5
XS GIS Cut Line= 2
     1872444.892      196110.167     1871920.256      196369.185
#Sta/Elev= 30
       0  2072.1    14.9 2064.94    39.7 2051.66    64.5 2036.98    94.2  2018.2
   104.1 2014.19     124 2007.18   143.8 2001.64   163.6 1997.48   193.4  1992.7
   218.2 1985.97   252.9 1975.09   270.7 1972.09   282.6 1971.64   285.7 1971.67
   292.6 1972.02   297.5 1972.76   322.3 1978.38   327.3 1980.02   342.1 1987.23
     352 1991.45   376.8 2000.87   401.6 2008.23   416.5 2011.05   426.4 2013.54
   466.1  2026.2   510.7 2041.67   530.6  2047.5   575.2 2064.53   585.1 2068.86
#Mann= 3 , 0 , 0
       0      .1       0   270.7    .045       0   285.7      .1       0
Bank Sta=270.7,285.7
XS Rating Curve= 0 ,0
Exp/Cntr=0.3,0.1

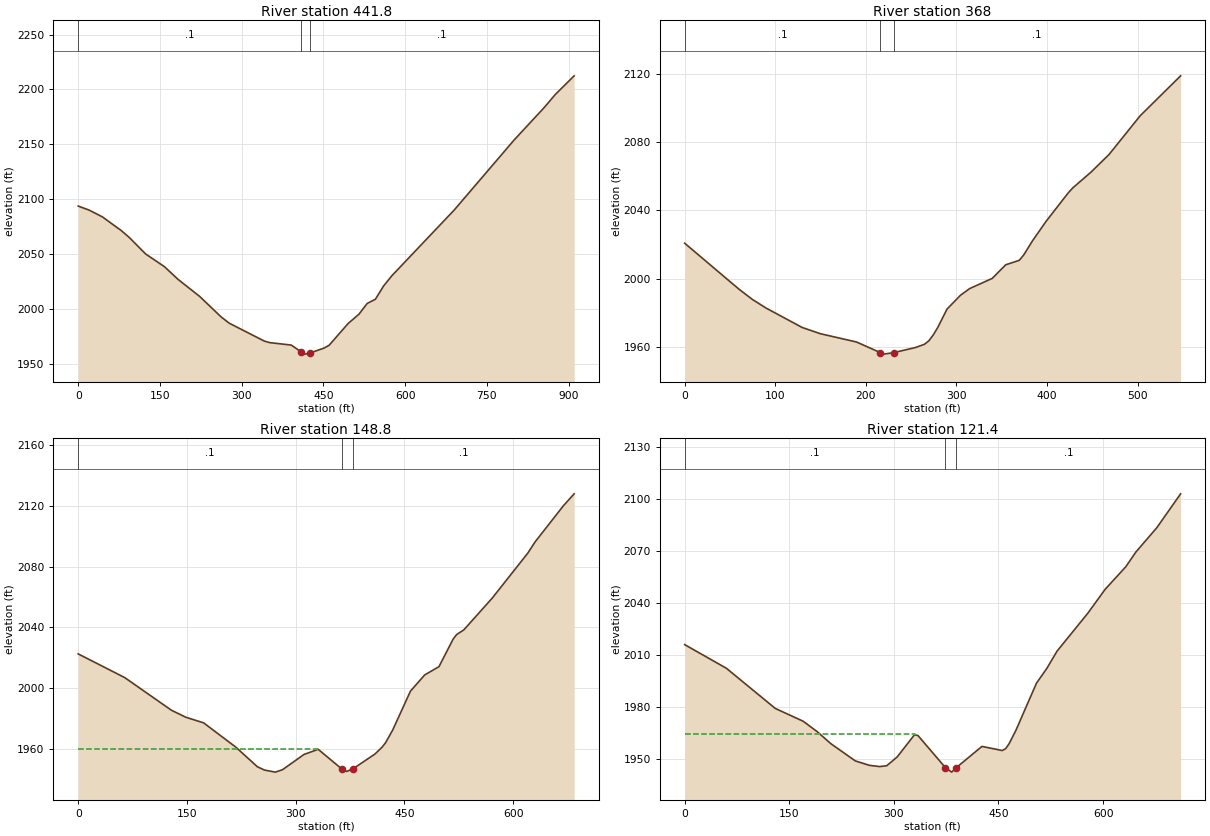
Type RM Length L Ch R = 1 ,441.8   ,70.9,73.9,76.9
XS GIS Cut Line= 3
     1872533.927      195873.871     1872086.055      195955.856
      1871637.97      196033.714
#Sta/Elev= 30
       0 2093.96    19.8 2090.32    44.5 2084.08    79.2  2071.6      94 2065.25
   123.7 2050.39   158.4 2038.76   183.1 2027.33   222.7 2011.84   262.3  1993.1
   277.2 1987.39   341.5 1971.15   351.4 1969.74     391  1967.5   409.6 1961.19
   415.7 1959.27   424.6 1960.21   450.4  1964.6   460.3 1967.26   495.3 1987.11
   515.3 1995.66   530.3 2005.36   545.3 2009.17   560.3 2021.16   575.3 2030.42
   690.2 2090.46   800.2 2154.19   855.1 2183.53   875.1 2195.23   910.1 2212.42
#Mann= 3 , 0 , 0
       0      .1       0   409.6    .045       0   424.6      .1       0
Bank Sta=409.6,424.6
XS Rating Curve= 0 ,0
Exp/Cntr=0.3,0.1

Type RM Length L Ch R = 1 ,368     ,252.3,219.1,220.8
XS GIS Cut Line= 3
     1872343.545      195864.759      1871994.35      195881.294
     1871803.703      195934.792
#Sta/Elev= 30
       0 2020.81    59.9 1993.94    74.9 1987.87    89.9 1982.87   129.8  1971.5
   149.8 1967.88   189.8 1963.01   215.8 1956.87   219.7 1955.93   230.8  1956.8
   254.7 1959.77   264.7 1961.67   269.7 1963.77   274.7 1967.33   279.7 1971.79
   289.7 1982.29   304.6 1990.39   314.6 1994.24   339.6 2000.23   354.5 2008.19
   369.4 2010.78   374.3 2013.88   384.2 2022.32   399.1 2033.64   423.8 2050.44
   428.8 2053.28   448.6 2062.36   468.4  2072.6     503 2095.38   547.6 2118.71
#Mann= 3 , 0 , 0
       0      .1       0   215.8    .045       0   230.8      .1       0
Bank Sta=215.8,230.8
XS Rating Curve= 0 ,0
Exp/Cntr=0.3,0.1

Type RM Length L Ch R = 1 ,148.8   ,20.4,27.4,34.5
XS GIS Cut Line= 4
     1872412.606      195777.216     1872091.619      195718.855
     1871985.596      195737.336     1871754.096       195832.66
#Sta/Elev= 30
       0 2022.57    64.3 2006.93   128.5 1985.49   148.3 1980.87     173 1977.15
   217.5 1961.13   247.2 1948.22     257 1946.06   271.9 1944.69   281.8 1946.26
   311.4  1956.3   331.1 1959.71     364 1946.65   370.3 1945.15     379 1946.83
   409.4 1956.61   419.2 1961.12   424.1  1964.1   433.9 1972.45   458.4 1998.06
     478 2008.71   497.7 2014.16   517.3 2032.35   522.2 2035.36     532 2038.38
   571.3 2059.38   620.4 2089.03   630.2 2096.26   669.5 2120.21   684.2    2128
#Mann= 3 , 0 , 0
       0      .1       0     364    .045       0     379      .1       0
#XS Ineff= 2 , 0
          331.09 1960.03
Permanent Ineff=
       F       F
Bank Sta=364,379
XS Rating Curve= 0 ,0
Exp/Cntr=0.3,0.1

Type RM Length L Ch R = 1 ,121.4   ,106.6,121.4,140.2
XS GIS Cut Line= 4
     1872428.764      195737.468     1872095.562      195706.512
     1871980.948      195690.421     1871740.486      195791.485
#Sta/Elev= 30
       0 2015.97    59.9  2002.3   129.9 1979.16   169.8 1971.79   189.8 1965.83
   209.8 1958.76   244.7 1948.88   264.7 1946.34   279.7  1945.6   289.7 1946.09
   304.7 1951.14   329.6 1963.99   334.6  1963.5     374 1944.95   382.9  1942.4
     389 1944.82   426.3 1957.24   455.3 1954.86   460.2  1955.9   465.1 1958.69
     475 1966.51   504.5 1993.73   519.3 2002.21     534  2012.2   578.3 2034.17
   602.9 2047.85   632.5 2060.85   647.2 2069.46   676.8 2083.28   711.2 2102.97
#Mann= 3 , 0 , 0
       0      .1       0     374    .045       0     389      .1       0
#XS Ineff= 2 , 0
           330.2 1964.46
Permanent Ineff=
       F       F
Bank Sta=374,389
XS Rating Curve= 0 ,0
Exp/Cntr=0.3,0.1

Chan Stop Cuts=-1
Use User Specified Reach Order=0